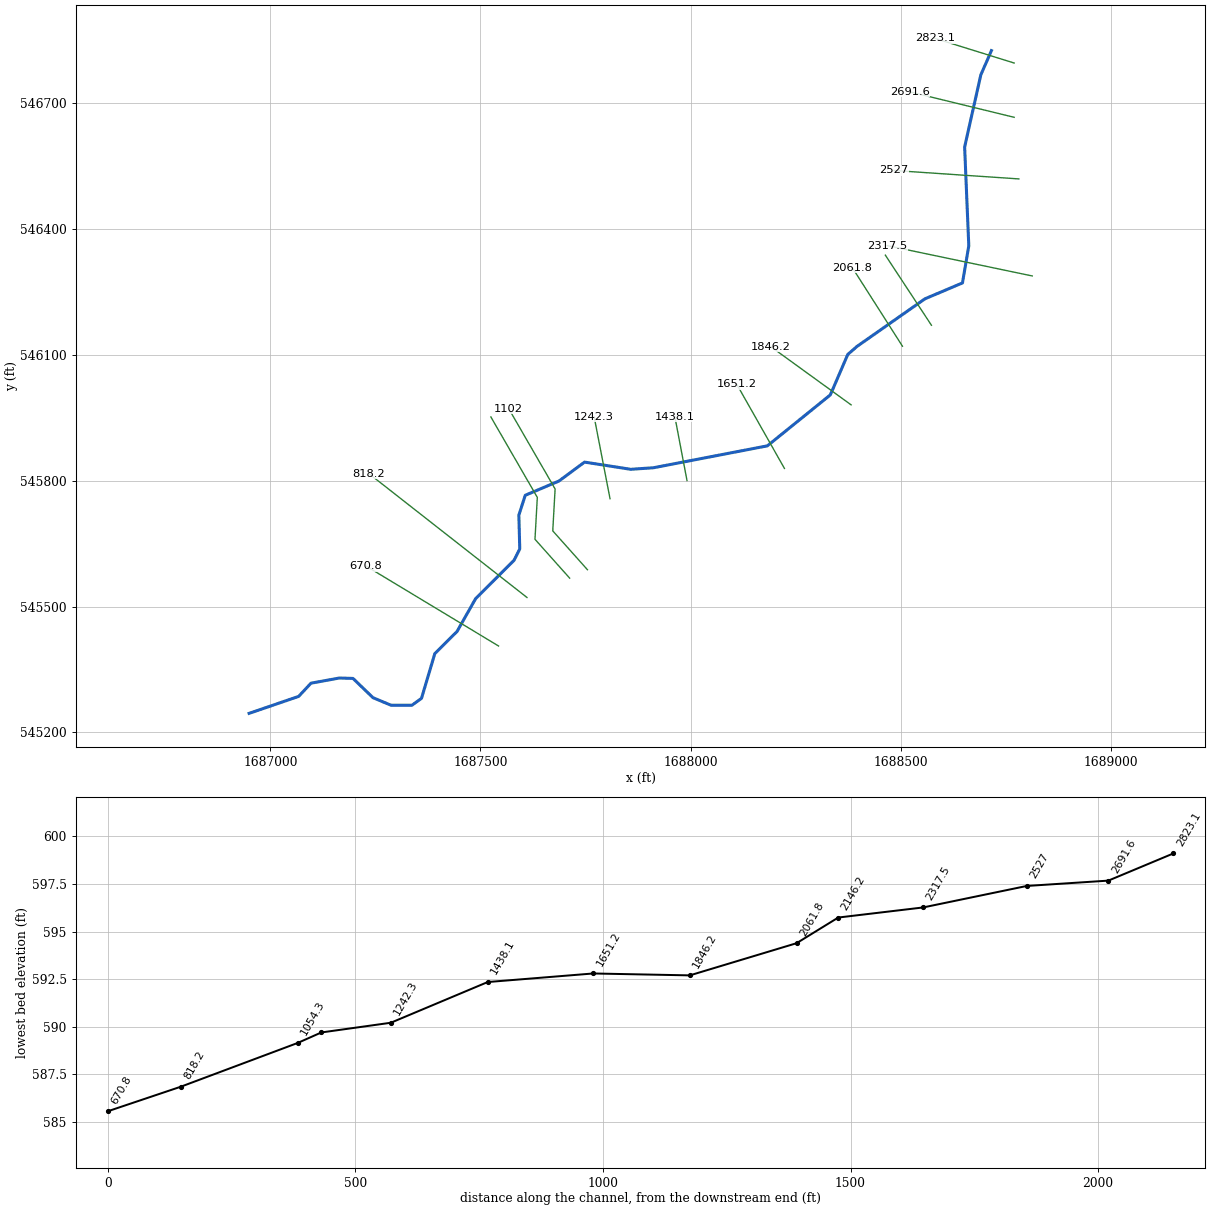
--- SugarBr.prj (project) ---

Proj Title=SugarBr
Current Plan=p01
Default Exp/Contr=0,0
English Units
Geom File=g01
Flow File=f01
Plan File=p01
BEGIN DESCRIPTION:
AMEC Environment & Infrastructure, 2013
Projection: NAD 1983 State Plane West Virginia South FIPS 4702 (US Feet)
Vertical Datum: NAVD 1988
END DESCRIPTION:
DSS Export Rating Curves= 0
DSS Export Rating Curve Sorted= 0
DSS Export Volume Flow Curves= 0
DXF OffsetX= 0
DXF OffsetY= 0
DXF ScaleX= 0
DXF ScaleY= 0

--- SugarBr.p01 (plan) ---

Plan Title=Floodplain
Program Version=4.00
Geom File=g01
Flow File=f01
K Sum by GR=0
Std Step Tol=0.01
Critical Tol=0.01
Num of Std Step Trials=20
Max Error Tol=0.3
Flow Tol Ratio=0.001
Split Flow NTrial=30
Split Flow Tol=0.02
Split Flow Ratio=0.02
Log Output Level=0
Friction Slope Method=1
Unsteady Friction Slope Method=2
Unsteady Bridges Friction Slope Method=1
Global Log Level=0
CheckData=False
Run HTab=0
Run UNet=0
Run PostProcess=0
UNET Theta=0
UNET Theta Warmup=0
UNET ZTol=0
UNET ZSATol=0
UNET MxIter=0
UNET MaxInSteps=0
UNET DtIC=0
UNET DtMin=0
UNET MaxCRTS=0
UNET WFStab=0
UNET SFStab=0
UNET WFX=0
UNET SFX=0
UNET DSS MLevel=0
UNET DZMax Abort=0
UNET Convert EG Bridges=0
UNET Use Existing IB Tables=0
UNET Froude Limit=0
UNET Froude Power=0
Write IC File=0
Echo Input=False
Echo Output=False
Write Detailed=0

--- SugarBr.f01 (steady flow) ---

Flow Title=USGS Regress. Eqn. (2010) - Western-Plateaus
Program Version=4.10
Number of Profiles= 1
Profile Names=P100yr
River Rch & RM=SugarBr,Main            ,2823.1
     888
River Rch & RM=SugarBr,Main            ,1438.1
     935
Boundary for River Rch & Prof#=SugarBr,Main            , 1
Up Type= 0
Dn Type= 3
Dn Slope=0.00901
DSS Import GetInterval= 0
DSS Import GetPeak= 0
DSS Import FillOption= 0

--- SugarBr.g01 (geometry) ---

Geom Title=USGS 3m DEM
Program Version=4.10

River Reach=SugarBr         ,Main
Reach XY= 30
     1688715.481      546825.437     1688690.244      546767.681
      1688651.71      546595.716     1688661.599      546360.129
     1688646.567      546271.652     1688557.432      546233.827
     1688395.974      546120.545     1688373.785       546101.22
     1688332.172       546004.66     1688182.459       545883.28
     1687911.269      545831.009      1687857.35      545827.358
     1687747.536      545844.504     1687686.499      545799.315
     1687606.462      545765.381     1687591.286      545718.202
     1687593.396      545637.561     1687579.779      545610.356
     1687488.422      545518.983     1687444.251      545440.795
     1687391.336      545387.975     1687359.655      545281.319
     1687336.993      545264.909     1687287.152      545264.905
     1687244.182      545282.951     1687196.754      545328.795
     1687164.248       545329.78     1687096.774      545317.467
     1687067.389      545285.947     1686949.457      545245.488

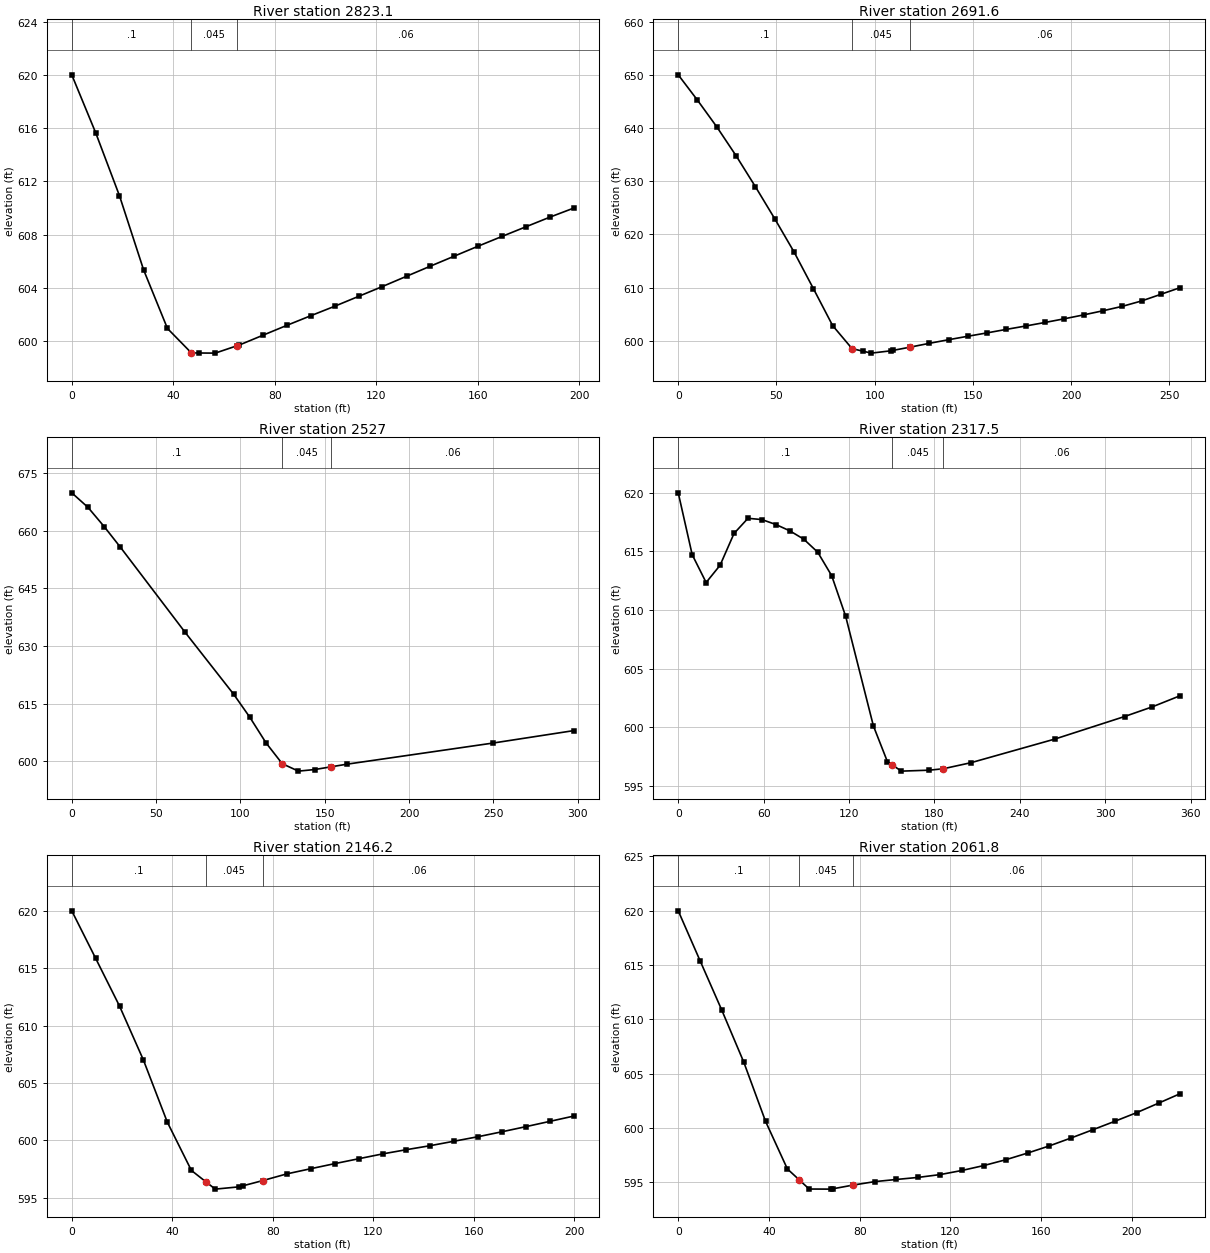
Type RM Length L Ch R = 1 ,2823.1  ,130.2,131.5,132.8
XS GIS Cut Line= 2
     1688769.576      546795.889     1688580.752      546854.752
#Sta/Elev= 24
       0     620     9.4  615.66    18.8  610.92    28.3  605.36    37.7  600.96
    47.1  599.13    50.2  599.12    56.5  599.11    65.2  599.67    65.9  599.71
    75.4  600.46    84.8   601.2    94.2  601.92   103.6  602.63     113  603.37
   122.4  604.11   131.9  604.88   141.3  605.64   150.7  606.39   160.1  607.14
   169.5  607.87     179   608.6   188.4  609.32   197.8     610
#Mann= 3 , 0 , 0
       0      .1       0    47.1    .045       0    65.2     .06       0
Bank Sta=47.1,65.2
XS Rating Curve= 0 ,0
Exp/Cntr=0.3,0.1

Type RM Length L Ch R = 1 ,2691.6  ,160.7,164.6,168.5
XS GIS Cut Line= 2
     1688769.576      546666.493     1688521.321      546727.176
#Sta/Elev= 29
       0     650     9.8  645.23    19.7  640.18    29.5  634.76    39.3  628.96
    49.2   622.9      59  616.67    68.8  609.81    78.6  602.86    88.5  598.52
    94.1  598.04    98.3  597.68   108.1  598.11   109.1  598.18     118   598.8
   127.8  599.52   137.6   600.2   147.4  600.85   157.3  601.49   167.1  602.15
   176.9  602.78   186.8  603.45   196.6  604.14   206.4  604.87   216.2  605.64
   226.1  606.48   235.9  607.49   245.7  608.74   255.6     610
#Mann= 3 , 0 , 0
       0      .1       0    88.5    .045       0     118     .06       0
Bank Sta=88.5,118
XS Rating Curve= 0 ,0
Exp/Cntr=0.3,0.1

Type RM Length L Ch R = 1 ,2527    ,211.6,209.5,205.3
XS GIS Cut Line= 2
     1688780.738      546519.609     1688483.713      546539.692
#Sta/Elev= 15
       0  669.91     9.6  666.13    19.2  661.12    28.8  655.76    67.2  633.57
      96  617.43   105.6  611.42   115.2  604.75   124.8  599.33   134.4   597.4
     144  597.81   153.6  598.51   163.3  599.22   249.7  604.71   297.7  607.96
#Mann= 3 , 0 , 0
       0      .1       0   124.8    .045       0   153.6     .06       0
Bank Sta=124.8,153.6
XS Rating Curve= 0 ,0
Exp/Cntr=0.3,0.1

Type RM Length L Ch R = 1 ,2317.5  ,189.2,171.4,152.7
XS GIS Cut Line= 2
     1688812.602      546288.257     1688467.446      546360.609
#Sta/Elev= 24
       0  619.98     9.8  614.71    19.6  612.34    29.4  613.81    39.2  616.52
      49  617.81    58.8   617.7    68.6  617.28    78.4  616.74    88.2  616.03
      98  614.92   107.8  612.92   117.6  609.47   137.1  600.12   146.9  597.09
   150.4   596.8   156.7  596.27   176.3  596.35   186.1  596.47   205.7  596.99
   264.5     599   313.5  600.92   333.1  601.75   352.7   602.7
#Mann= 3 , 0 , 0
       0      .1       0   150.4    .045       0   186.1     .06       0
Bank Sta=150.4,186.1
XS Rating Curve= 0 ,0
Exp/Cntr=0.3,0.1

Type RM Length L Ch R = 1 ,2146.2  ,84.6,84.3,83.9
XS GIS Cut Line= 2
     1688572.726      546170.794     1688463.107      546337.817
#Sta/Elev= 24
       0     620     9.5  615.86      19   611.7    28.5     607      38  601.59
    47.6  597.37    53.3  596.39    57.1  595.74    66.6  595.94    68.3  596.04
    76.1  596.49    85.6  597.07    95.1  597.52   104.6  597.96   114.2  598.39
   123.7  598.81   133.2  599.18   142.7  599.53   152.2  599.92   161.7  600.31
   171.2  600.74   180.8  601.19   190.3  601.65   199.8  602.11
#Mann= 3 , 0 , 0
       0      .1       0    53.3    .045       0    76.1     .06       0
Bank Sta=53.3,76.1
XS Rating Curve= 0 ,0
Exp/Cntr=0.3,0.1

Type RM Length L Ch R = 1 ,2061.8  ,207,215.6,224.1
XS GIS Cut Line= 2
     1688503.829      546120.746     1688384.964      546307.422
#Sta/Elev= 26
       0     620     9.6  615.42    19.2  610.86    28.9  606.07    38.5  600.62
    48.1  596.25    53.4  595.23    57.7   594.4    67.4  594.39    68.4  594.43
      77  594.76    86.6  595.08    96.2  595.28   105.8  595.47   115.5  595.73
   125.1  596.11   134.7  596.56   144.3  597.09     154  597.71   163.6  598.37
   173.2   599.1   182.8  599.86   192.4  600.63   202.1  601.43   211.7   602.3
   221.3  603.18
#Mann= 3 , 0 , 0
       0      .1       0    53.4    .045       0      77     .06       0
Bank Sta=53.4,77
XS Rating Curve= 0 ,0
Exp/Cntr=0.3,0.1

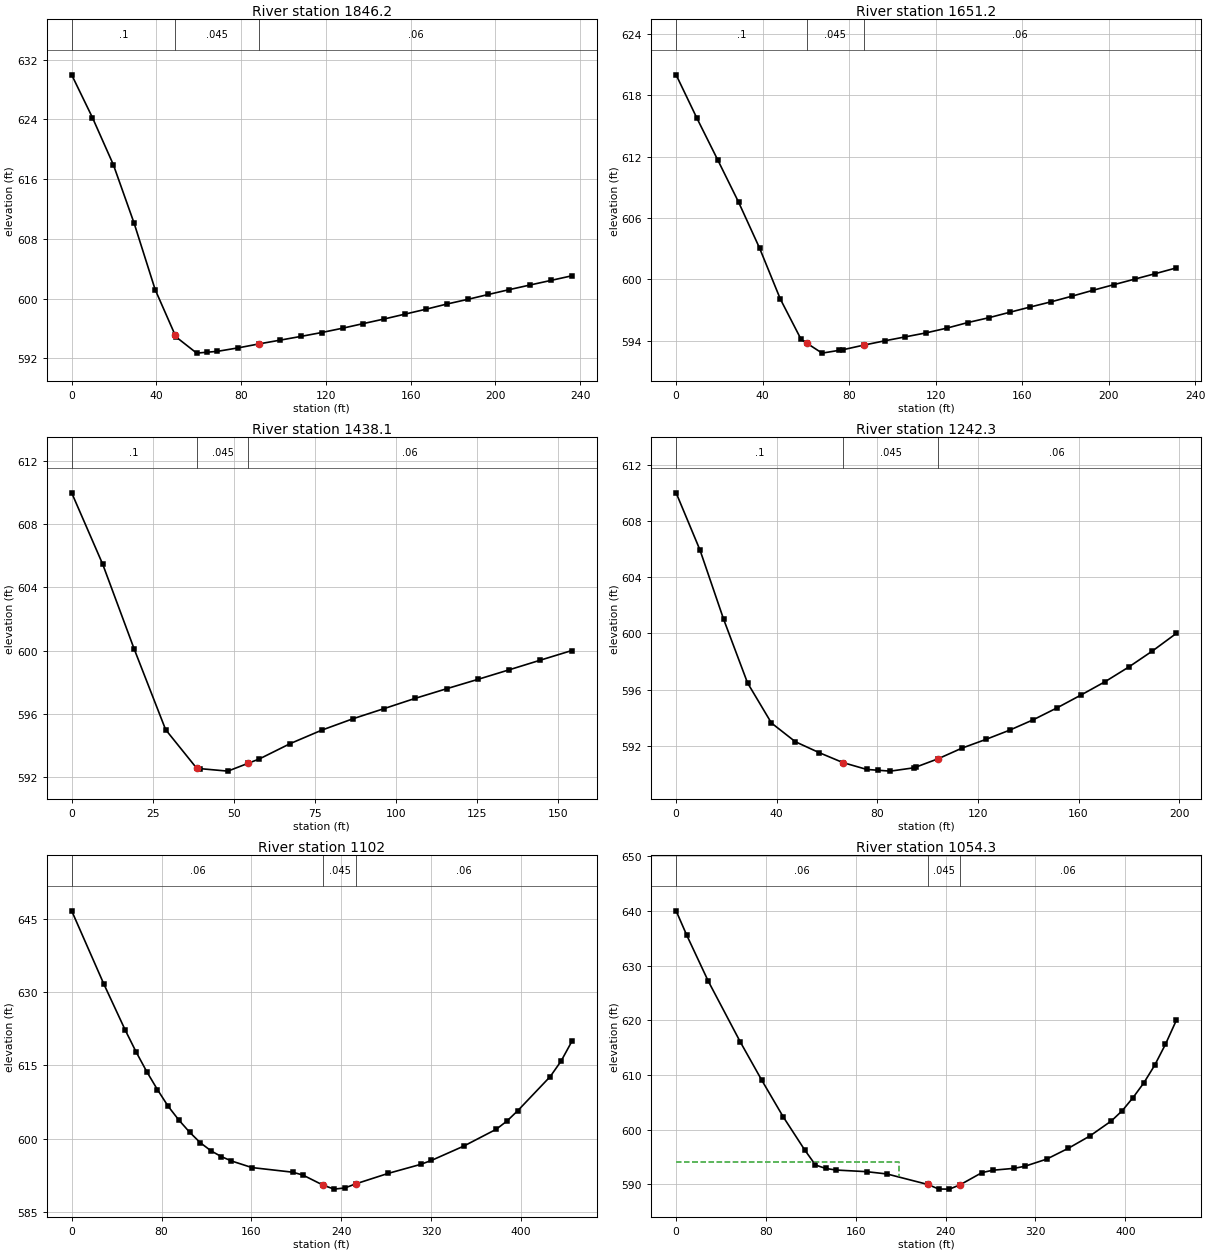
Type RM Length L Ch R = 1 ,1846.2  ,204.5,195.1,185
XS GIS Cut Line= 2
      1688381.73      545980.941     1688190.702      546119.643
#Sta/Elev= 27
       0  629.98     9.8  624.25    19.7  617.92    29.5  610.08    39.4  601.21
    48.8  595.14    49.2  594.88      59   592.7    63.8  592.82    68.8  592.94
    78.7  593.41    88.5  593.94    98.4  594.44   108.2  594.94     118  595.46
   127.9  596.04   137.7  596.66   147.6  597.28   157.4  597.93   167.2  598.58
     177  599.27   186.9   599.9   196.7  600.56   206.6  601.21   216.4  601.83
   226.2  602.44   236.1  603.06
#Mann= 3 , 0 , 0
       0      .1       0    48.8    .045       0    88.5     .06       0
Bank Sta=48.8,88.5
XS Rating Curve= 0 ,0
Exp/Cntr=0.3,0.1

Type RM Length L Ch R = 1 ,1651.2  ,220.4,213,205.6
XS GIS Cut Line= 2
     1688223.133      545829.315     1688109.308      546030.639
#Sta/Elev= 27
       0     620     9.6  615.77    19.3  611.66    28.9  607.55    38.6  603.06
    48.2  598.08    57.8  594.14    60.3  593.79    67.5   592.8    75.3  593.07
    77.1  593.13    86.7  593.58    96.4     594     106  594.39   115.6  594.78
   125.3  595.25   134.9  595.79   144.6  596.26   154.2  596.79   163.8  597.31
   173.5  597.82   183.1  598.37   192.7  598.94   202.4  599.49     212  600.03
   221.6  600.57   231.3  601.13
#Mann= 3 , 0 , 0
       0      .1       0    60.3    .045       0    86.7     .06       0
Bank Sta=60.3,86.7
XS Rating Curve= 0 ,0
Exp/Cntr=0.3,0.1

Type RM Length L Ch R = 1 ,1438.1  ,193.5,195.8,197.6
XS GIS Cut Line= 2
     1687991.264      545800.542     1687962.491      545952.219
#Sta/Elev= 19
       0     610     9.6  605.46    19.3  600.09      29  594.98    38.6  592.53
    39.5  592.51    48.2  592.35    54.5  592.85    57.9  593.12    67.5   594.1
    77.2  594.95    86.8  595.67    96.5  596.32   106.1  596.97   115.8  597.58
   125.4  598.17   135.1  598.78   144.7  599.39   154.4     600
#Mann= 3 , 0 , 0
       0      .1       0    38.6    .045       0    54.5     .06       0
Bank Sta=38.6,54.5
XS Rating Curve= 0 ,0
Exp/Cntr=0.3,0.1

Type RM Length L Ch R = 1 ,1242.3  ,137.3,140.3,146.5
XS GIS Cut Line= 2
     1687808.152      545757.277     1687770.382      545952.526
#Sta/Elev= 24
       0  609.99     9.5  605.92    18.9     601    28.4  596.48    37.9  593.63
    47.4   592.3    56.8  591.53    66.3  590.82    75.8  590.33    80.4  590.27
    85.2  590.21    94.7  590.45    95.4   590.5   104.2  591.09   113.6  591.84
   123.1  592.46   132.6  593.12     142  593.86   151.5  594.71     161  595.62
   170.5  596.56   179.9   597.6   189.4  598.75   198.9     600
#Mann= 3 , 0 , 0
       0      .1       0    66.3    .045       0   104.2     .06       0
Bank Sta=66.3,104.2
XS Rating Curve= 0 ,0
Exp/Cntr=0.3,0.1

Type RM Length L Ch R = 1 ,1102    ,46.7,47.6,47.1
XS GIS Cut Line= 4
      1687754.44      545587.941     1687671.906      545680.596
     1687677.478       545780.51     1687566.967      545972.264
#Sta/Elev= 30
       0  646.61    28.6  631.66    47.7  622.22    57.3  617.79    66.8  613.75
    76.4  610.04    85.9  606.65    95.4  603.84     105  601.35   114.5   599.2
   124.1  597.53   133.2  596.36   142.3  595.46   160.5  594.11   196.9  593.16
     206  592.57   224.2  590.48   233.8   589.7   243.4  589.95     253  590.78
   281.9  592.92   310.8  594.76   320.4  595.57   349.2   598.5   378.1  601.94
   387.7  603.63   397.4  605.77   426.2  612.72   435.8  615.86   445.5  619.93
#Mann= 3 , 0 , 0
       0     .06       0   224.2    .045       0     253     .06       0
Bank Sta=224.2,253
XS Rating Curve= 0 ,0
Exp/Cntr=0.3,0.1

Type RM Length L Ch R = 1 ,1054.3  ,224.9,236.1,244.3
XS GIS Cut Line= 4
     1687712.148      545567.848     1687629.614      545660.503
     1687635.186      545760.417     1687524.675      545952.171
#Sta/Elev= 30
       0     640     9.5  635.53    28.6  627.16    57.3  615.99    76.4  609.01
    95.4  602.35   114.5  596.32   124.1  593.56   133.2  592.93   142.3  592.64
   169.6  592.34   187.8  591.92   224.2     590   233.8  589.17   243.4  589.15
     253  589.95   272.3  592.16   281.9   592.6   301.1  592.95   310.8  593.34
     330  594.63   349.2   596.6   368.5  598.86   387.7  601.62   397.4   603.5
     407  605.89   416.6  608.58   426.2  611.78   435.8  615.61   445.5     620
#Mann= 3 , 0 , 0
       0     .06       0   224.2    .045       0     253     .06       0
#XS Ineff= 2 , 0
          198.59   594.1
Permanent Ineff=
       F       F
Bank Sta=224.2,253
XS Rating Curve= 0 ,0
Exp/Cntr=0.3,0.1

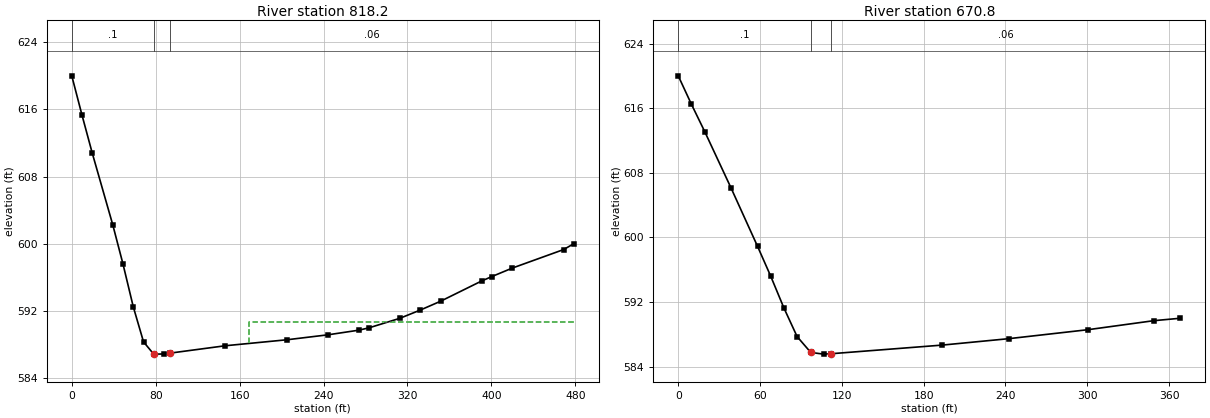
Type RM Length L Ch R = 1 ,818.2   ,144.4,147.4,150
XS GIS Cut Line= 2
     1687610.602      545521.756     1687234.146      545817.322
#Sta/Elev= 24
       0  619.99     9.8  615.29    19.5   610.8    39.1  602.24    48.8  597.59
    58.6   592.5    68.4  588.31    78.1  586.85    78.7  586.85    87.9  586.87
    93.7  586.97   146.5  587.85   205.1  588.56   244.2  589.15   273.5   589.7
   283.3  589.98   312.6  591.11   332.1  592.09   351.6  593.15   390.7  595.56
   400.5  596.09     420   597.1   468.8   599.3   478.6     600
#Mann= 3 , 0 , 0
       0      .1       0    78.7    .045       0    93.7     .06       0
#XS Ineff= 2 , 0
                          169.01          590.69
Permanent Ineff=
       F       F
Bank Sta=78.7,93.7
XS Rating Curve= 0 ,0
Exp/Cntr=0.3,0.1

Type RM Length L Ch R = 1 ,670.8   ,684,670.8,661
XS GIS Cut Line= 2
        1687543.      545406.087     1687227.833      545596.624
#Sta/Elev= 16
       0     620     9.7  616.47    19.4  613.11    38.8   606.1    58.2  598.89
    67.8  595.22    77.5  591.28    87.2  587.73    97.2  585.77   106.6  585.56
   112.2  585.61   193.8  586.68   242.3  587.47   300.4  588.58   348.9   589.7
   368.3     590
#Mann= 3 , 0 , 0
       0      .1       0    97.2    .045       0   112.2     .06       0
Bank Sta=97.2,112.2
XS Rating Curve= 0 ,0
Exp/Cntr=0.3,0.1

Chan Stop Cuts=-1
Use User Specified Reach Order=0
Composite Channel Slope=5